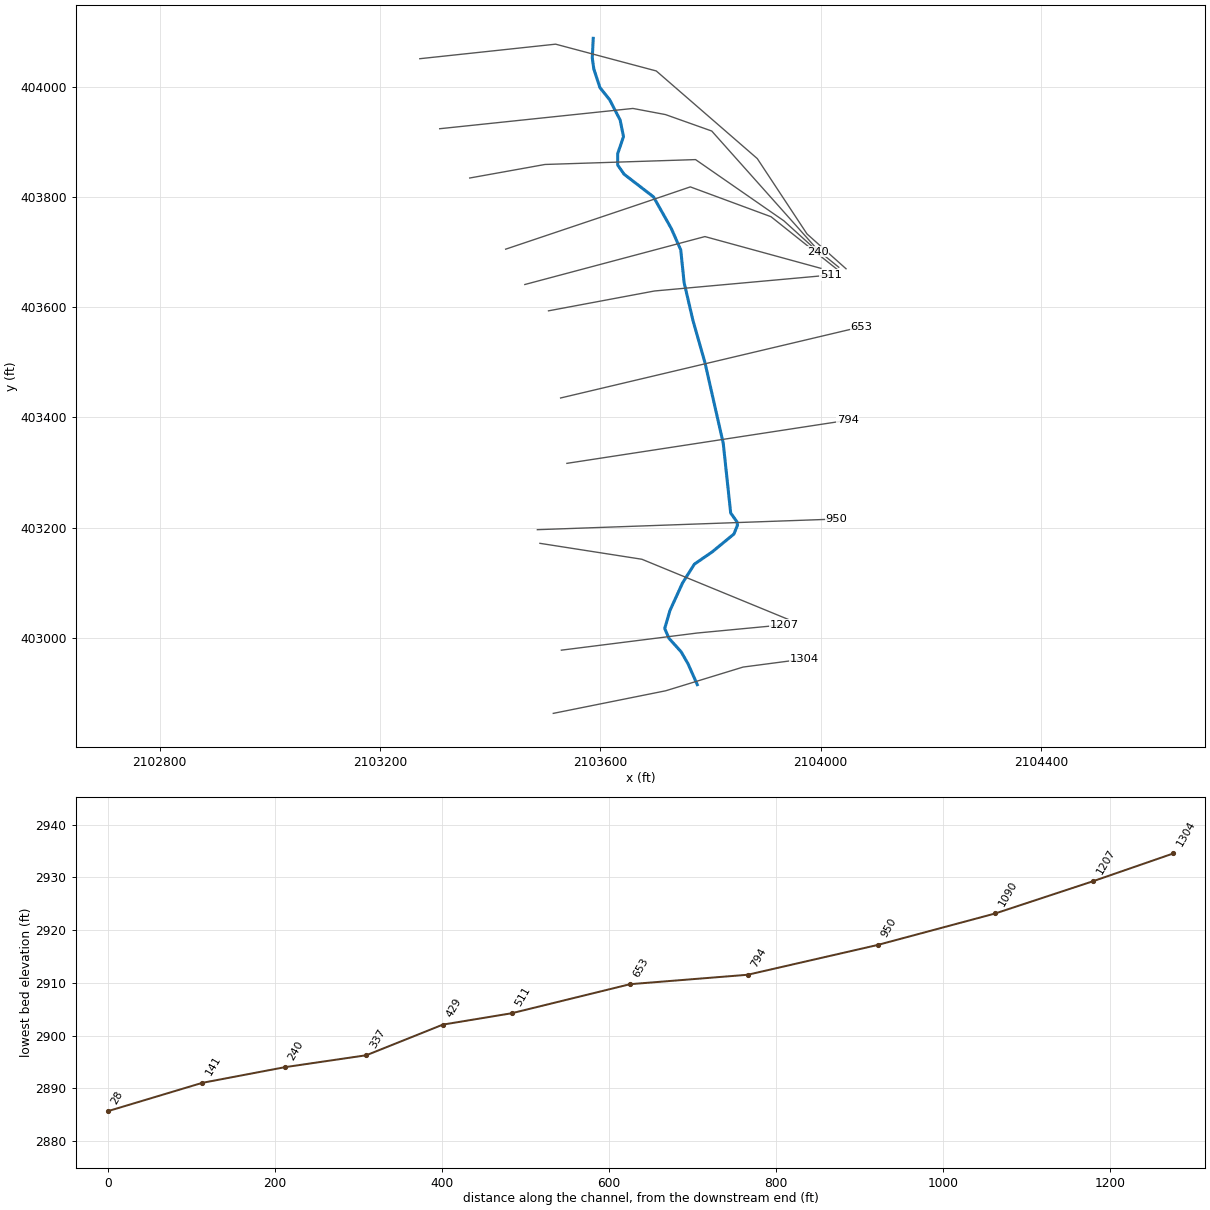
--- JOBKNOBBR2.prj (project) ---

Proj Title=JOBKNOBBR2
Current Plan=p01
Default Exp/Contr=0.3,0.1
English Units
Geom File=g01
Flow File=f01
Plan File=p01
Y Axis Title=Elevation
X Axis Title(PF)=Main Channel Distance
X Axis Title(XS)=Station
BEGIN DESCRIPTION:
Stream Name- Job Knob Branch 2
Flood Zone: Zone A
Greenbrier County, WV
County-Wide Study
WVDHSEM-2018-3, Flood Risk Project
HEC-RAS Version: 5.0.7
General Notes:
For the Hydrology regression was used.
END DESCRIPTION:
DSS Export Rating Curves= 0
DSS Export Rating Curve Sorted= 0
DSS Export Volume Flow Curves= 0
DXF Filename=JOBKNOBBR2.M2.
DXF OffsetX= 0
DXF OffsetY= 0
DXF ScaleX= 1
DXF ScaleY= 10

--- JOBKNOBBR2.p01 (plan) ---

Plan Title=Floodplain
Program Version=5.07
Short Identifier=Floodplain
Geom File=g01
Flow File=f01
Subcritical Flow
K Sum by GR= 0
Std Step Tol= 0.01
Critical Tol= 0.01
Num of Std Step Trials= 20
Max Error Tol= 0.3
Flow Tol Ratio= 0.001
Split Flow NTrial= 30
Split Flow Tol= 0.02
Split Flow Ratio= 0.02
Log Output Level= 0
Friction Slope Method= 1
Unsteady Friction Slope Method= 2
Unsteady Bridges Friction Slope Method= 1
Parabolic Critical Depth
Global Vel Dist= 0 , 0 , 0
Global Log Level= 0
CheckData=True
Encroach Param=-1 ,0,0, 0
Computation Interval=1MIN
Output Interval=1HOUR
Instantaneous Interval=1HOUR
Mapping Interval=1HOUR
Computation Time Step Use Courant=        0
Computation Time Step Use Time Series=    0
Computation Time Step Count To Double=0
Computation Time Step Max Doubling=0
Computation Time Step Max Halving=0
Computation Time Step Residence Courant=0
Run HTab= 0
Run UNet= 0
Run Sediment= 0
Run PostProcess= 0
Run WQNet= 0
Run RASMapper= 0
UNET Theta= 1
UNET Theta Warmup= 1
UNET ZTol= 0.02
UNET ZSATol= 0.02
UNET MxIter= 20
UNET Max Iter WO Improvement= 0
UNET MaxInSteps= 0
UNET DtIC= 0
UNET DtMin= 0
UNET MaxCRTS= 20
UNET WFStab= 2
UNET SFStab= 1
UNET WFX= 1
UNET SFX= 1
UNET 1D Methodology=Finite Difference
UNET DSS MLevel= 4
UNET Pardiso=0
UNET DZMax Abort= 100
UNET Use Existing IB Tables=-1
UNET Froude Reduction=False
UNET Froude Limit= 0.8
UNET Froude Power= 4
UNET D1 Cores= 0
UNET D2 Coriolis=0
UNET D2 Cores= 0
UNET D2 Theta= 1
UNET D2 Theta Warmup= 1
UNET D2 Z Tol= 0.01
UNET D2 Volume Tol= 0.01
UNET D2 Max Iterations= 20
UNET D2 Equation= 0
UNET D2 RampUpFraction=0.1
UNET D2 TimeSlices= 1
UNET D2 BCVolumeCheck=0
UNET D1D2 MaxIter= 0
UNET D1D2 ZTol=0.01
UNET D1D2 QTol=0.1
UNET D1D2 MinQTol=1
Write IC File= 0
Write IC File at Fixed DateTime=0
Write IC File at Sim End=0
Echo Input=False
Echo Parameters=False
Echo Output=False
Write Detailed= 0
HDF Write Warmup=0
HDF Write Time Slices=0
HDF Flush=0
HDF Face Node Velocities=0
HDF Compression= 1
HDF Chunk Size= 1
HDF Spatial Parts= 1
HDF Use Max Rows=0
HDF Fixed Rows= 1
Calibration Method= 0
Calibration Iterations= 20
Calibration Max Change=0.05
Calibration Tolerance=0.2
Calibration Maximum=1.5
Calibration Minimum=0.5
Calibration Optimization Method= 1
WQ AD Non Conservative
WQ ULTIMATE=-1
WQ Max Comp Step=1HOUR
WQ Output Interval=15MIN
WQ Output Selected Increments= 0
WQ Output face flow=0
WQ Output face velocity=0
WQ Output face area=0
WQ Output face dispersion=0
WQ Output cell volume=0
WQ Output cell surface area=0
WQ Output cell continuity=0
WQ Output cumulative cell continuity=0
WQ Output face conc=0
WQ Output face dconc_dx=0
WQ Output face courant=0
WQ Output face peclet=0
WQ Output face adv mass=0
WQ Output face disp mass=0
WQ Output cell mass=0
WQ Output cell source sink temp=0
WQ Output nsm pathways=0
WQ Output nsm derived pathways=0
WQ Output MaxMinRange=-1
WQ Daily Max Min Mean=-1
WQ Daily Range=0
WQ Daily Time=0
WQ Create Restart=0
WQ Fixed Restart=0
WQ System Summary=0
WQ Write To DSS=0
WQ Use Fixed Temperature=0
Sorting and Armoring Iterations= 10
XS Update Threshold= 0.02
Bed Roughness Predictor= 0
Hydraulics Update Threshold= 0.02
Energy Slope Method= 1
Volume Change Method= 1
Sediment Retention Method= 0
XS Weighting Method= 0
Number of US Weighted Cross Sections= 1
Number of DS Weighted Cross Sections= 1
Upstream XS Weight=0
Main XS Weight=1
Downstream XS Weight=0
Number of DS XS's Weighted with US Boundary= 1
Upstream Boundary Weight= 1
Weight of XSs Associated with US Boundary= 0
Number of US XS's Weighted with DS Boundary= 1
Downstream Boundary Weight= 0.5
Weight of XSs Associated with DS Boundary= 0.5
Percentile Method= 0
Sediment Output Level= 3
Mass or Volume Output= 0
Output Increment Type= 1
Profile and TS Output Increment= 1
XS Output Flag= 0
XS Output Increment= 10
Write Gradation File= 0
Read Gradation Hotstart= 0
Write HDF5 File= 1
Write Binary Output= 1
Write DSS Sediment File= 0
SV Curve= 0
Specific Gage Flag= 0

--- JOBKNOBBR2.f01 (steady flow) ---

Flow Title=Flow
Program Version=5.07
Number of Profiles= 6
Profile Names=f1p,f10p,f4p,f2p,f02p,f1pplus
River Rch & RM=BEECHRN1,Main            ,6099
     536     283     376     454     750     793
River Rch & RM=BEECHRN1,Main            ,4642
     659     350     465     559     919     975
River Rch & RM=COLDSPRBR,Main            ,7507
     515     271     361     436     721     762
River Rch & RM=COLDSPRBR,Main            ,7028
     574     303     403     486     802     849
River Rch & RM=COLDSPRBR,Main            ,2967
     657     349     463     557     916     972
River Rch & RM=COLDSPRBR,Main            ,1721
     734     392     518     623    1020    1090
River Rch & RM=HOGCMPRN,Main            ,4263
     557     294     391     472     779     824
River Rch & RM=HOGCMPRN,Main            ,3068
     638     338     449     540     889     943
River Rch & RM=JOBKNOBBR2,Main            ,1304
     458     240     321     387     643     678
River Rch & RM=JOBKNOBBR2,Main            ,794
     623     330     439     528     869     922
River Rch & RM=MCMILLCK,Main            ,13233
     571     302     401     483     798     844
River Rch & RM=MCMILLCK,Main            ,9424
     651     346     459     552     907     963
River Rch & RM=MCMILLCK,Main            ,7089
     735     392     519     624    1020    1090
River Rch & RM=MCMILLCK,Main            ,4416
     823     441     583     699    1140    1220
River Rch & RM=MIDDLEBR,Main            ,9120
     499     262     350     422     699     738
River Rch & RM=MIDDLEBR,Main            ,8068
     633     300     399     480     793     839
River Rch & RM=MIDDLEBR,Main            ,6306
     633     336     445     536     882     936
Boundary for River Rch & Prof#=BEECHRN1,Main            , 1
Up Type= 0
Dn Type= 3
Dn Slope=0.035
Boundary for River Rch & Prof#=BEECHRN1,Main            , 2
Up Type= 0
Dn Type= 3
Dn Slope=0.035
Boundary for River Rch & Prof#=BEECHRN1,Main            , 3
Up Type= 0
Dn Type= 3
Dn Slope=0.035
Boundary for River Rch & Prof#=BEECHRN1,Main            , 4
Up Type= 0
Dn Type= 3
Dn Slope=0.035
Boundary for River Rch & Prof#=BEECHRN1,Main            , 5
Up Type= 0
Dn Type= 3
Dn Slope=0.035
Boundary for River Rch & Prof#=BEECHRN1,Main            , 6
Up Type= 0
Dn Type= 3
Dn Slope=0.035
Boundary for River Rch & Prof#=COLDSPRBR,Main            , 1
Up Type= 0
Dn Type= 3
Dn Slope=0.036398
Boundary for River Rch & Prof#=COLDSPRBR,Main            , 2
Up Type= 0
Dn Type= 3
Dn Slope=0.036398
Boundary for River Rch & Prof#=COLDSPRBR,Main            , 3
Up Type= 0
Dn Type= 3
Dn Slope=0.036398
Boundary for River Rch & Prof#=COLDSPRBR,Main            , 4
Up Type= 0
Dn Type= 3
Dn Slope=0.036398
Boundary for River Rch & Prof#=COLDSPRBR,Main            , 5
Up Type= 0
Dn Type= 3
Dn Slope=0.036398
Boundary for River Rch & Prof#=COLDSPRBR,Main            , 6
Up Type= 0
Dn Type= 3
Dn Slope=0.036398
Boundary for River Rch & Prof#=HOGCMPRN,Main            , 1
Up Type= 0
Dn Type= 3
Dn Slope=0.02
Boundary for River Rch & Prof#=HOGCMPRN,Main            , 2
Up Type= 0
Dn Type= 3
Dn Slope=0.02
Boundary for River Rch & Prof#=HOGCMPRN,Main            , 3
Up Type= 0
Dn Type= 3
Dn Slope=0.02
Boundary for River Rch & Prof#=HOGCMPRN,Main            , 4
Up Type= 0
Dn Type= 3
Dn Slope=0.02
Boundary for River Rch & Prof#=HOGCMPRN,Main            , 5
Up Type= 0
Dn Type= 3
Dn Slope=0.02
Boundary for River Rch & Prof#=HOGCMPRN,Main            , 6
Up Type= 0
Dn Type= 3
Dn Slope=0.02
Boundary for River Rch & Prof#=JOBKNOBBR2,Main            , 1
Up Type= 0
Dn Type= 3
Dn Slope=0.043277
Boundary for River Rch & Prof#=JOBKNOBBR2,Main            , 2
Up Type= 0
Dn Type= 3
Dn Slope=0.043277
Boundary for River Rch & Prof#=JOBKNOBBR2,Main            , 3
Up Type= 0
Dn Type= 3
Dn Slope=0.043277
Boundary for River Rch & Prof#=JOBKNOBBR2,Main            , 4
Up Type= 0
Dn Type= 3
Dn Slope=0.043277
Boundary for River Rch & Prof#=JOBKNOBBR2,Main            , 5
Up Type= 0
Dn Type= 3
Dn Slope=0.043277
Boundary for River Rch & Prof#=JOBKNOBBR2,Main            , 6
Up Type= 0
Dn Type= 3
Dn Slope=0.043277
Boundary for River Rch & Prof#=MCMILLCK,Main            , 1
Up Type= 0
Dn Type= 3
Dn Slope=0.03585
Boundary for River Rch & Prof#=MCMILLCK,Main            , 2
Up Type= 0
Dn Type= 3
Dn Slope=0.03585
Boundary for River Rch & Prof#=MCMILLCK,Main            , 3
Up Type= 0
Dn Type= 3
Dn Slope=0.03585
Boundary for River Rch & Prof#=MCMILLCK,Main            , 4
Up Type= 0
Dn Type= 3
Dn Slope=0.03585
Boundary for River Rch & Prof#=MCMILLCK,Main            , 5
Up Type= 0
Dn Type= 3
Dn Slope=0.03585
Boundary for River Rch & Prof#=MCMILLCK,Main            , 6
Up Type= 0
Dn Type= 3
Dn Slope=0.03585
Boundary for River Rch & Prof#=MIDDLEBR,Main            , 1
Up Type= 0
Dn Type= 3
Dn Slope=0.083839
Boundary for River Rch & Prof#=MIDDLEBR,Main            , 2
Up Type= 0
Dn Type= 3
Dn Slope=0.083839
Boundary for River Rch & Prof#=MIDDLEBR,Main            , 3
Up Type= 0
Dn Type= 3
Dn Slope=0.083839
Boundary for River Rch & Prof#=MIDDLEBR,Main            , 4
Up Type= 0
Dn Type= 3
Dn Slope=0.083839
Boundary for River Rch & Prof#=MIDDLEBR,Main            , 5
Up Type= 0
Dn Type= 3
Dn Slope=0.083839
Boundary for River Rch & Prof#=MIDDLEBR,Main            , 6
Up Type= 0
Dn Type= 3
Dn Slope=0.083839
DSS Import GetInterval= 0
DSS Import GetPeak= 0
DSS Import FillOption= 0

--- JOBKNOBBR2.g01 (geometry) ---

Geom Title=Geometry
Program Version=5.07

River Reach=JOBKNOBBR2      ,Main
Reach XY= 30
2103776.02179551402914.9202235492103759.14682928402952.836814374
2103746.85518718402974.2951048022103724.56356511402999.087049961
 2103716.8552472403016.7953478842103726.43856135403049.503615797
 2103749.3551822403099.711848706 2103770.8134726 403133.67011413
2103802.68840885 403155.545070382103842.48032403403188.253666371
2103848.93864444403204.2953009612103848.10531276403210.336955547
2103836.64700237403226.3785901222103823.10536277403353.045331538
2103789.86920878403499.6286997942103768.20258543403575.739768043
 2103752.0913972403644.6284097882103745.98018894403704.072844714
2103728.75811052403742.9618745452103696.53573403403800.184201047
2103643.20250735403841.2953393012103631.53586403403857.961972624
2103631.53586403403878.517377704 2103642.0912891403909.628535956
2103635.98008084403939.6284759642103617.09133911403976.295069292
2103599.31348753  403998.51746582103588.20228928404032.406177551
2103585.42473578404052.4064656352103587.18162203404087.949373543

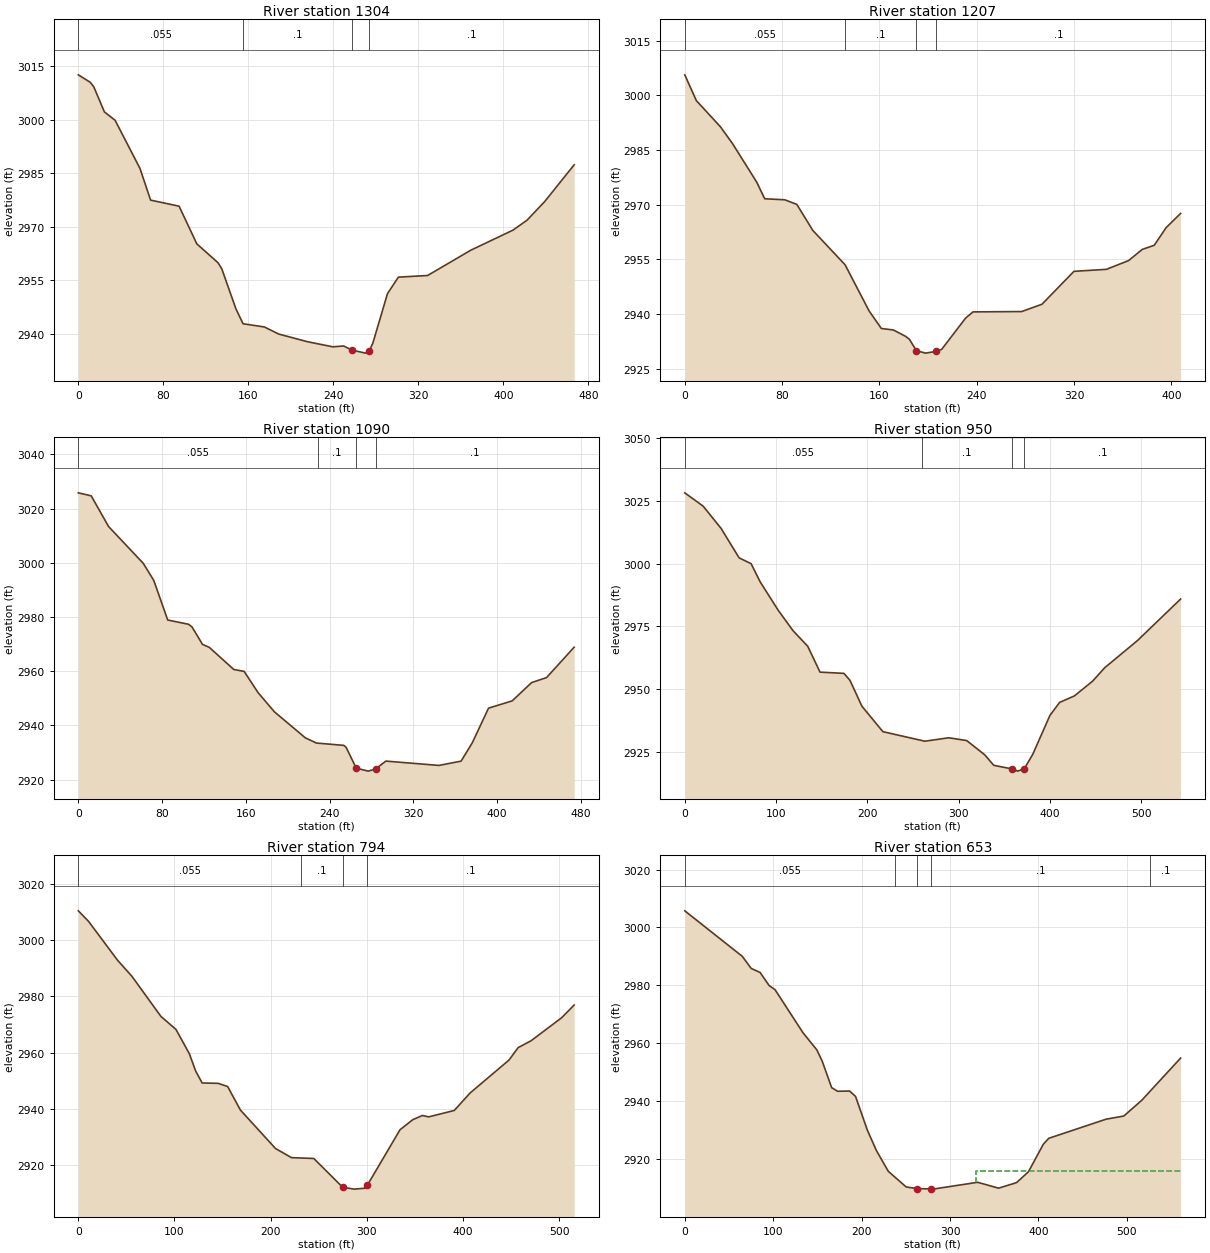
Type RM Length L Ch R = 1 ,1304    ,96.6,96.4,93.9
XS GIS Cut Line= 4
2103514.66142586402862.7700653822103718.59376079402903.764077872
2103859.21880761 402946.833873632103969.74712986402961.363372132
#Sta/Elev= 30
       0 3012.62    11.1 3010.55    14.5 3009.29    24.5 3002.23    34.6 2999.87
      58 2986.37      68 2977.47    94.8 2975.77   111.5  2965.2   131.6 2959.86
     135  2958.2   148.3 2946.96     155 2942.78   175.1 2941.88   188.5  2939.9
   215.5 2937.75   239.5 2936.31   249.7 2936.55   257.6 2935.38   270.3 2934.54
   273.8 2935.19   277.2 2937.38   290.9 2951.21   301.2 2955.86   328.7 2956.32
   369.3 2963.41     409 2969.04   422.3 2971.85   438.8 2977.04   466.6 2987.37
#Mann= 4 ,-1 , 0
       0    .055       0   154.9      .1       0   257.6    .045       0
   273.8      .1       0
Bank Sta=257.6,273.8
XS Rating Curve= 0 ,0
Exp/Cntr=0.3,0.1

Type RM Length L Ch R = 1 ,1207    ,119.3,117.1,110.8
XS GIS Cut Line= 3
2103529.32051727402977.503431708 2103775.9870187403008.614589959
2103934.32036343403023.614559963
#Sta/Elev= 30
       0 3005.65     9.5 2998.57    29.3 2991.39    39.2  2986.8    59.1 2976.22
    65.7 2971.63    82.2 2971.35    92.1 2970.09   105.3 2962.93   131.8 2953.51
   151.6 2940.81   161.6 2936.03   171.5 2935.61   181.4  2933.9   184.7 2933.06
  190.382929.958   197.9 2929.26   206.7 2929.74   211.2 2930.29     231 2938.91
     237 2940.58     277 2940.67   293.7 2942.68     320 2951.71   346.7 2952.26
   364.9 2954.66   376.1 2957.72     386 2958.86   395.8 2963.71   407.7 2967.61
#Mann= 4 ,-1 , 0
       0    .055       0   131.8      .1       0  190.38    .045       0
   206.7      .1       0
Bank Sta=190.38,206.7
XS Rating Curve= 0 ,0
Exp/Cntr=0.3,0.1

Type RM Length L Ch R = 1 ,1090    ,140,140.8,143.4
XS GIS Cut Line= 3
2103490.43148744403171.3924796282103675.43144551  403142.5034298
2103940.43157169403033.614539966
#Sta/Elev= 30
       0  3025.8    12.3 3024.69    28.9 3013.37      62 2999.81    72.1 2993.48
    85.4 2978.89   105.3 2977.32   108.6 2976.33   118.6 2969.92   125.2 2968.78
   148.5 2960.64   158.4 2959.94   171.7 2952.12   187.2 2945.08   216.8 2935.45
   227.4 2933.51   253.6 2932.65   255.8 2931.96   265.5 2924.24   277.1 2923.15
   284.2 2923.98   293.8 2926.85   344.5 2925.25   365.7 2926.84   376.4 2933.61
   391.9 2946.37   414.5 2949.07   433.1 2955.82   447.3 2957.64   473.7 2968.86
#Mann= 4 ,-1 , 0
       0    .055       0  228.66      .1       0   265.5    .045       0
   284.2      .1       0
Bank Sta=265.5,284.2
XS Rating Curve= 0 ,0
Exp/Cntr=0.3,0.1

Type RM Length L Ch R = 1 ,950     ,154.4,155.4,156.3
XS GIS Cut Line= 2
2103485.76089311403196.1663802122104028.84806153403215.499674872
#Sta/Elev= 30
       0 3028.24    20.1 3022.93    39.8 3014.03    59.5  3002.3    72.7 2999.96
    82.5 2992.78   102.2 2981.47   118.6 2973.23   134.7 2967.03   148.2 2956.69
   174.4 2956.19     181 2953.43   194.1  2943.1   217.1 2932.93   263.1 2929.12
   289.3 2930.49     309 2929.37   328.7  2923.7   338.6  2919.5   358.3 2918.09
   364.8 2917.18  372.08 2918.14   381.3 2923.84   400.2 2939.43   410.8 2944.61
     427  2947.2   446.9 2953.07   460.1  2958.4   496.2 2969.32   543.4 2985.86
#Mann= 4 ,-1 , 0
       0    .055       0  260.02      .1       0   358.3    .045       0
  372.08      .1       0
Bank Sta=358.3,372.08
XS Rating Curve= 0 ,0
Exp/Cntr=0.3,0.1

Type RM Length L Ch R = 1 ,794     ,140.2,140.9,142.3
XS GIS Cut Line= 2
2103539.36675704403316.5595121232104049.05996335403394.771297961
#Sta/Elev= 30
       0 3010.34    10.6 3006.61    40.7 2992.85    55.8 2987.07    85.9 2972.86
   101.6 2968.22   115.5 2959.58   122.1 2953.41   128.8 2949.22   145.4  2949.1
   155.3 2947.97   168.6  2939.6   205.1 2925.96   221.7 2922.71   244.9 2922.42
   274.8 2912.24   286.8 2911.54   298.1 2911.86  300.53 2912.88   334.6 2932.63
   347.8 2936.18   357.8 2937.68   364.4 2937.19     391 2939.46   407.4 2945.65
     448 2957.38   457.4 2961.76     471 2964.24   502.7 2972.39   515.7  2976.9
#Mann= 4 ,-1 , 0
       0    .055       0  231.18      .1       0   274.8    .045       0
  300.53      .1       0
Bank Sta=274.8,300.53
XS Rating Curve= 0 ,0
Exp/Cntr=0.3,0.1

Type RM Length L Ch R = 1 ,653     ,143.2,141.8,140.1
XS GIS Cut Line= 2
2103527.94256726403435.1951016342104073.66588527403564.375945628
#Sta/Elev= 30
       0 3005.75      65 2990.06    75.1 2985.88    85.2 2984.48    95.3 2980.01
   102.1 2978.54   133.6 2963.73   149.3 2957.81   155.4 2953.91   166.1 2944.76
   172.9  2943.5   186.4 2943.59   193.1 2941.74   206.6 2930.02   216.7 2923.08
   230.2 2915.89   250.4 2910.49   263.1 2909.93   278.1 2909.82   280.7 2909.75
   331.3 2912.11   354.9 2910.08   375.2 2911.99   388.7 2915.74   405.5 2925.23
   411.6 2927.27   476.3 2933.86   496.5 2934.96   516.8 2940.38   560.8 2954.96
#Mann= 5 ,-1 , 0
       0    .055       0  237.45      .1       0   263.1    .045       0
   278.1      .1       0  526.44      .1       0
#XS Ineff= 2 , 0
                          329.37         2916.13
Permanent Ineff=
       F       F
Bank Sta=263.1,278.1
XS Rating Curve= 0 ,0
Exp/Cntr=0.3,0.1

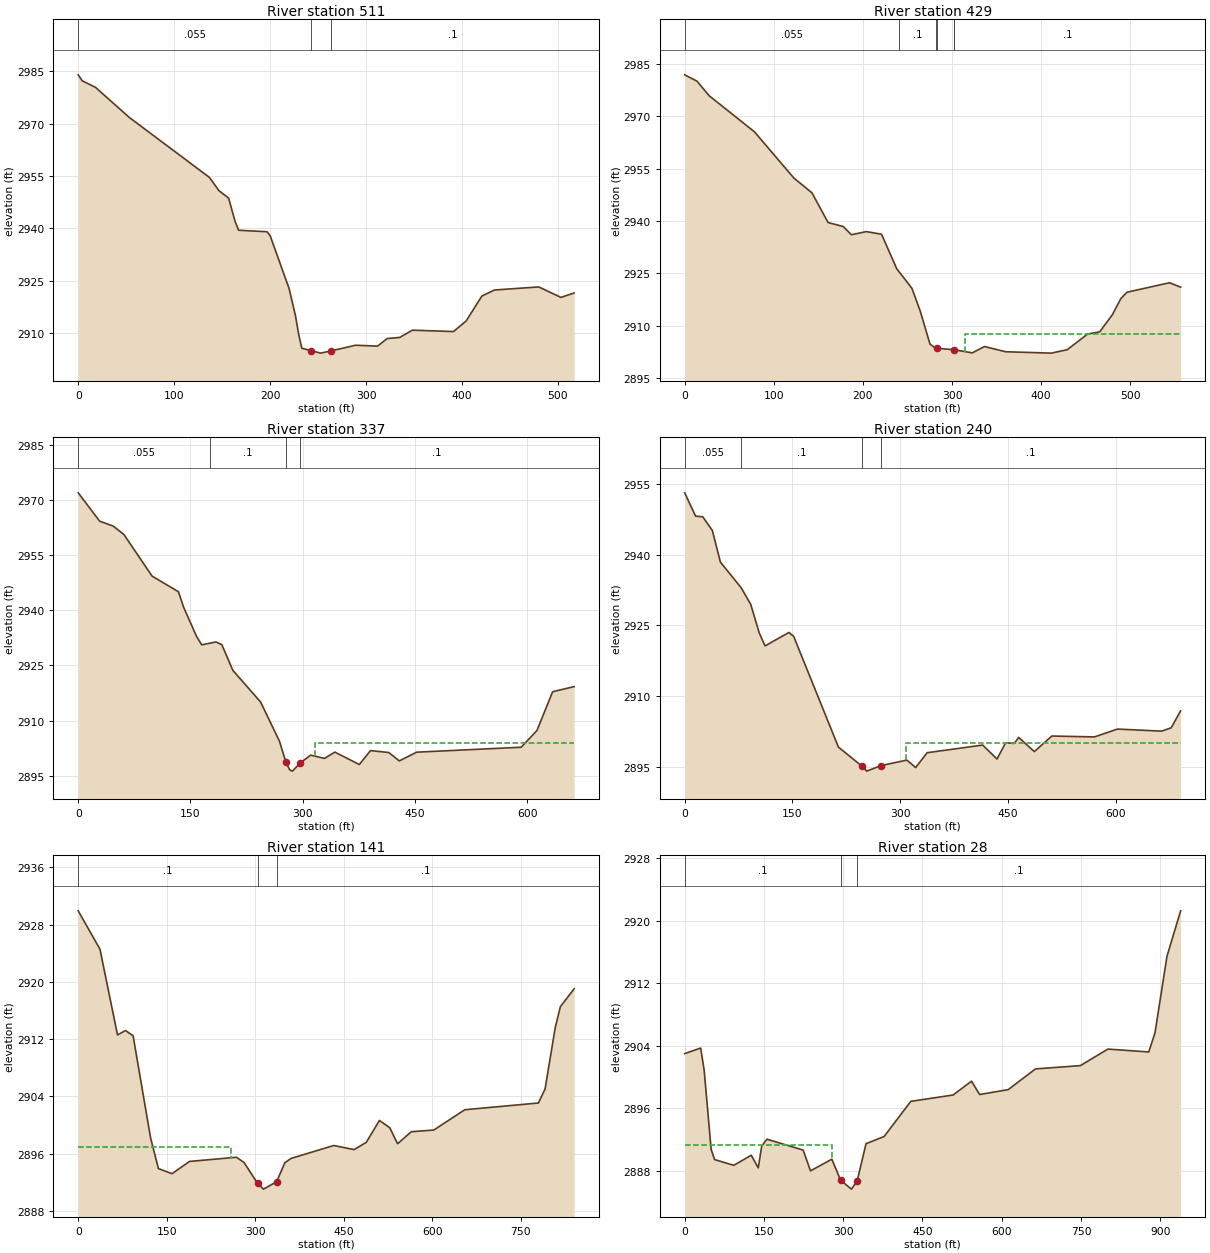
Type RM Length L Ch R = 1 ,511     ,81.3,82.3,84.5
XS GIS Cut Line= 3
2103505.97279495403593.375887632 2103698.4261502403629.405999288
2104018.30280703403658.405613214
#Sta/Elev= 30
       0 2983.99     4.2 2982.29    18.2 2980.36    53.3 2971.77   136.8 2954.59
   146.8 2950.77   156.8 2948.67   163.5 2942.03   167.2 2939.45   196.8 2939.03
   200.1 2937.89   219.9 2922.69   226.5 2914.94   229.8 2909.65   233.1 2905.64
     243 2904.94   252.7 2904.24   263.9 2904.89   289.1  2906.5   312.1 2906.25
     322 2908.41   335.2 2908.74   348.4 2910.82   391.2 2910.42   404.4 2913.44
   420.8 2920.59   433.9 2922.33   480.1 2923.21   503.2 2920.21     517 2921.48
#Mann= 3 ,-1 , 0
       0    .055       0     243    .045       0   263.9      .1       0
Bank Sta=243,263.9
XS Rating Curve= 0 ,0
Exp/Cntr=0.3,0.1

Type RM Length L Ch R = 1 ,429     ,91.9,91.7,93.3
XS GIS Cut Line= 3
 2103463.0197615403641.142954782 2103789.8582893403728.146076799
2104000.30094212403670.507045873
#Sta/Elev= 30
       0 2981.95    13.8 2980.14    27.4 2975.97    78.3 2965.59   122.4 2952.36
   142.8 2948.09   160.9 2939.56   177.9 2938.42     187 2936.06   203.8 2936.96
   220.9  2936.2   237.9 2926.31   254.9  2920.7   264.3 2914.15   275.2  2904.7
   281.6 2903.47   282.8 2903.49   302.4 2903.05   322.8 2902.17   336.3 2903.98
   360.1 2902.49   411.2 2902.09   429.1 2903.06     452 2907.56   465.6  2908.2
   479.8  2913.1   489.4 2917.76   496.2 2919.56   543.8 2922.28   556.4 2921.03
#Mann= 6 ,-1 , 0
       0    .055       0   240.8      .1       0   281.6      .1       0
   282.8    .045       0   302.4      .1       0   302.5      .1       0
#XS Ineff= 2 , 0
                          314.64         2907.51
Permanent Ineff=
       F       F
Bank Sta=282.8,302.4
XS Rating Curve= 0 ,0
Exp/Cntr(USF)=0,0
Exp/Cntr=0.3,0.1

Type RM Length L Ch R = 1 ,337     ,111.9,97.5,101
XS GIS Cut Line= 5
2103428.20949903403705.2811756282103675.98721868403788.614670381
2103763.34826443 403818.336723792103909.87618661403764.170165464
2104029.32050154403669.031248122
#Sta/Elev= 30
       0 2971.89    28.7 2964.18    46.8 2962.85    61.2 2960.53    98.6 2949.28
   133.9 2945.02   140.8 2940.83   158.1 2932.89     165 2930.59     184 2931.37
   191.9 2930.64   206.6 2923.66   243.7 2915.05   268.9 2904.39  277.482898.714
   282.5 2896.64   286.2 2896.28   296.6 2898.48   310.5 2900.63     329 2899.74
   342.9 2901.45   375.6 2898.07   390.5 2901.86     415 2901.33     429 2899.06
   452.2 2901.43   591.8 2902.77   612.9 2907.31   633.9 2917.86   662.6 2919.24
#Mann= 4 ,-1 , 0
       0    .055       0  175.51      .1       0  277.48    .045       0
   296.6      .1       0
#XS Ineff= 2 , 0
                          316.53         2903.99
Permanent Ineff=
       F       F
Bank Sta=277.48,296.6
XS Rating Curve= 0 ,0
Exp/Cntr=0.3,0.1

Type RM Length L Ch R = 1 ,240     ,97.1,98.9,100.2
XS GIS Cut Line= 5
2103362.99310903403834.4432960832103499.61864558403859.016234312
2103772.86971867403867.8624920742103933.08527592403756.792811282
2103994.61493033403700.976856472
#Sta/Elev= 30
       0 2953.17    15.2 2948.22    25.2 2948.07    38.5 2945.17    49.7 2938.45
    78.5 2933.02    91.9 2929.48   103.7 2923.43   111.8 2920.63   145.1 2923.49
   151.7 2922.66     214 2899.12   246.9 2895.06   253.4 2894.02   273.1 2895.19
   309.2 2896.36   321.5 2894.78   337.4 2897.93   414.7 2899.56   434.7  2896.6
   446.6 2900.03   458.6 2899.91   464.9 2901.18   486.6 2898.17     511 2901.48
   570.4 2901.29   602.3 2902.96   663.8 2902.52   677.1 2903.23   690.2 2906.83
#Mann= 4 ,-1 , 0
       0    .055       0    78.5      .1       0   246.9    .045       0
   273.1      .1       0
#XS Ineff= 2 , 0
                           307.4         2899.97
Permanent Ineff=
       F       F
Bank Sta=246.9,273.1
XS Rating Curve= 0 ,0
Exp/Cntr(USF)=0,0
Exp/Cntr=0.3,0.1

Type RM Length L Ch R = 1 ,141     ,121.9,113.3,112.1
XS GIS Cut Line= 6
2103308.48729753403923.8922869562103659.18147802403960.697987631
2103718.20924711403949.5867893842103802.23729429403919.725628629
2103996.68145919403701.6702904552104032.79260743403672.503682122
#Sta/Elev= 30
       0 2929.92    36.9 2924.55    66.6 2912.59    80.2  2913.2      93 2912.47
   122.7 2898.19   135.9 2893.92     159 2893.21   188.7 2894.92   268.1  2895.5
     281 2894.77  303.872891.868     314 2891.05  336.182892.075   350.2 2894.74
   360.7 2895.34   432.9 2897.14   467.5 2896.57   488.1 2897.58   510.5 2900.64
     528 2899.62   541.2 2897.39   564.5 2899.07   602.5  2899.3   655.2 2902.14
   779.9 2903.08   791.1 2905.03   808.4 2913.62   817.1 2916.54   840.4 2919.03
#Mann= 3 ,-1 , 0
       0      .1       0  303.87    .045       0  336.18      .1       0
#XS Ineff= 2 , 0
          258.06 2896.98
Permanent Ineff=
       F       F
Bank Sta=303.87,336.18
XS Rating Curve= 0 ,0
Exp/Cntr=0.3,0.1

Type RM Length L Ch R = 1 ,28      ,24.33,27.69,31.05
XS GIS Cut Line= 6
2103272.37614927404050.9756942092103518.90387145404077.364749044
2103701.54261377404028.7536257952103884.87590852403869.725728631
2103975.15394318 403732.920227962104045.98713484403669.725800544
#Sta/Elev= 30
       0 2903.02    30.3 2903.73    36.9 2900.88    50.1 2890.74    56.7 2889.45
      93 2888.72     126 2890.01   139.2 2888.39   145.8 2891.18   155.7 2892.06
   224.2 2890.67   238.1 2888.01   278.5  2889.5  295.082886.811   315.6 2885.67
   326.4 2886.72   343.2 2891.49   377.3  2892.4     428 2896.91     508 2897.72
   542.8 2899.49   558.1 2897.78   612.3 2898.41   663.8 2901.06   748.8 2901.48
   800.9  2903.6   878.2 2903.23     890 2905.67   912.7 2915.48   938.5  2921.3
#Mann= 3 , 0 , 0
       0      .1       0  295.08    .045       0   326.4      .1       0
#XS Ineff= 2 , 0
          277.87 2891.33
Permanent Ineff=
       F       F
Bank Sta=295.08,326.4
XS Rating Curve= 0 ,0
Exp/Cntr=0.3,0.1
LCMann Table=0

Chan Stop Cuts=-1
Use User Specified Reach Order=0
Composite Channel Slope=5